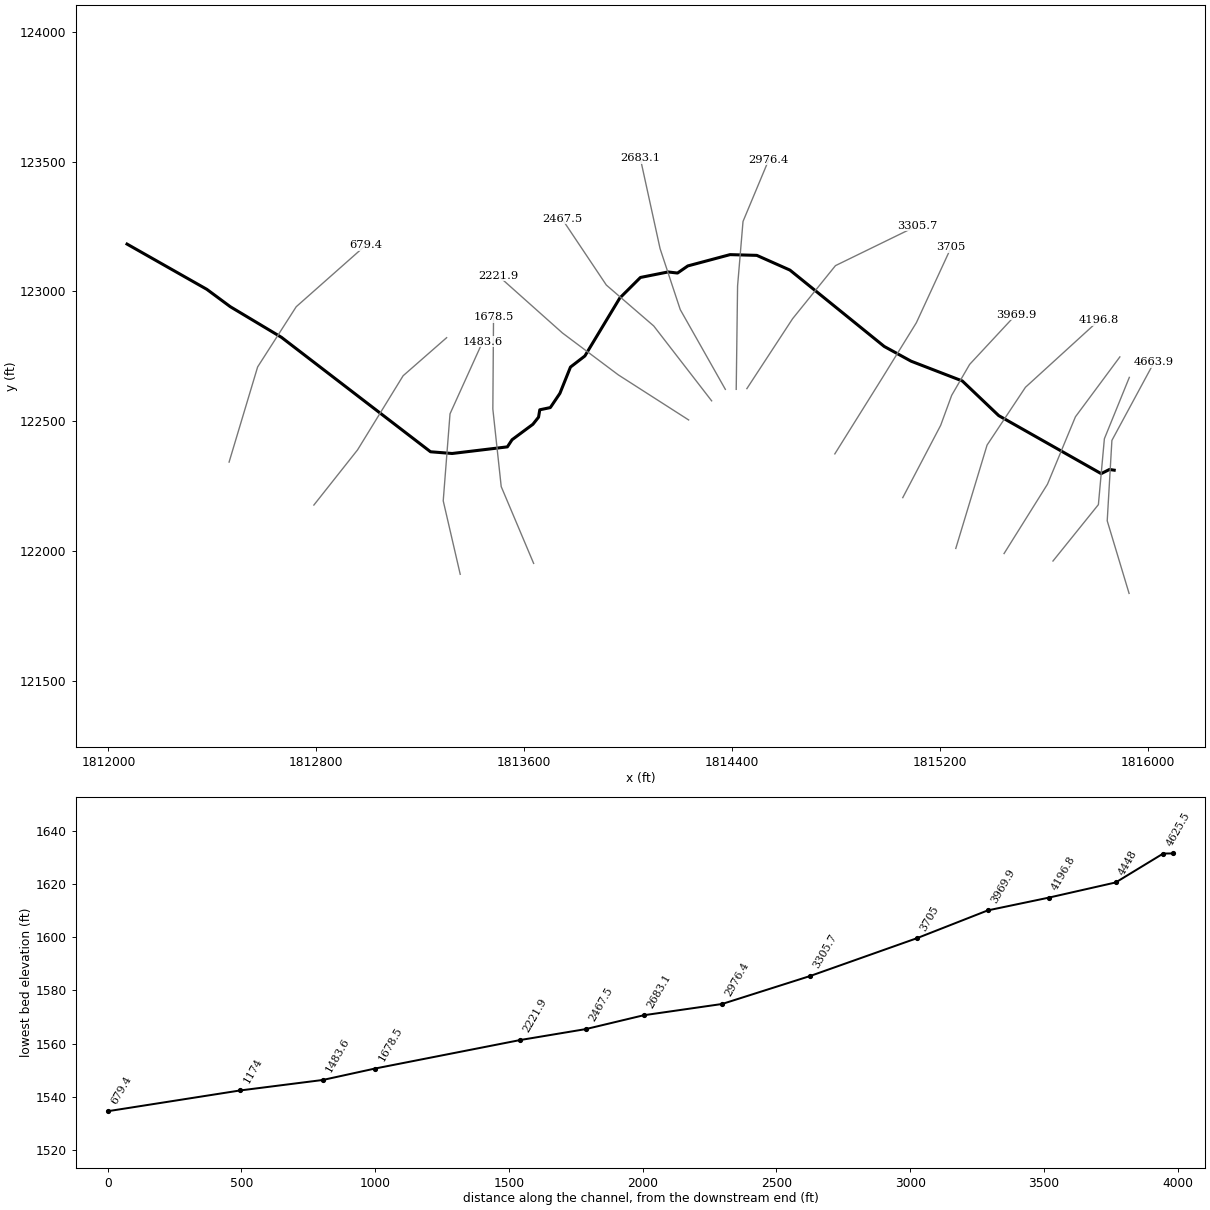
--- Left Fork Sandlick Creek.prj (project) ---

Proj Title=Left Fork Sandlick Creek
Current Plan=p01
Default Exp/Contr=0,0
English Units
Geom File=g01
Flow File=f01
Plan File=p01
BEGIN DESCRIPTION:
END DESCRIPTION:
DSS Export Rating Curves= 0
DSS Export Rating Curve Sorted= 0
DSS Export Volume Flow Curves= 0
DXF OffsetX= 0
DXF OffsetY= 0
DXF ScaleX= 0
DXF ScaleY= 0

--- Left Fork Sandlick Creek.p01 (plan) ---

Plan Title=Floodplain
Program Version=4.00
Geom File=g01
Flow File=f01
K Sum by GR=0
Std Step Tol=0.01
Critical Tol=0.01
Num of Std Step Trials=20
Max Error Tol=0.3
Flow Tol Ratio=0.001
Split Flow NTrial=30
Split Flow Tol=0.02
Split Flow Ratio=0.02
Log Output Level=0
Friction Slope Method=1
Unsteady Friction Slope Method=2
Unsteady Bridges Friction Slope Method=1
Global Log Level=0
CheckData=False
Run HTab=0
Run UNet=0
Run PostProcess=0
UNET Theta=0
UNET Theta Warmup=0
UNET ZTol=0
UNET ZSATol=0
UNET MxIter=0
UNET MaxInSteps=0
UNET DtIC=0
UNET DtMin=0
UNET MaxCRTS=0
UNET WFStab=0
UNET SFStab=0
UNET WFX=0
UNET SFX=0
UNET DSS MLevel=0
UNET DZMax Abort=0
UNET Convert EG Bridges=0
UNET Use Existing IB Tables=0
UNET Froude Limit=0
UNET Froude Power=0
Write IC File=0
Echo Input=False
Echo Output=False
Write Detailed=0

--- Left Fork Sandlick Creek.f01 (steady flow) ---

Flow Title=NFF Regression Equation
Program Version=4.00
Number of Profiles=1
Profile Names=P100yr
River Rch & RM=Left Fork San...,Main      ,4663.9
807.5637
River Rch & RM=Left Fork San...,Main      ,2976.4
837.4735
River Rch & RM=Left Fork San...,Main      ,2683.1
949.1884
River Rch & RM=Left Fork San...,Main      ,1483.6
986.1207
River Rch & RM=Left Fork San...,Main      ,1174
1128.583
Boundary for River Rch & Prof#=Left Fork San...,Main      ,1
Up Type=0
Dn Type=3
Dn Slope=0.016842

--- Left Fork Sandlick Creek.g01 (geometry) ---

Geom Title=USGS 10m DEM
Program Version=4.00

River Reach=Left Fork San...,Main
Reach XY= 30
     1815871.319      122312.176     1815853.099      122314.887
      1815821.01      122298.895     1815426.644      122522.263
      1815286.59      122655.584     1815089.624      122731.609
     1814986.001      122788.431     1814623.116       123082.33
      1814495.54       123139.03     1814392.534      123141.865
     1814229.992      123098.395     1814190.301      123070.989
     1814153.909       123075.17     1814047.604      123053.979
     1813968.191      122974.808     1813833.679       122751.71
     1813778.276       122709.05     1813737.641      122607.934
     1813700.785      122553.123      1813660.15      122544.618
     1813655.424      122516.268     1813633.689      122488.862
     1813553.363      122429.326     1813535.408      122401.921
      1813322.78      122376.406     1813239.619      122383.021
     1812665.819      122823.525     1812468.796      122941.472
     1812378.406      123008.375     1812071.323      123182.539

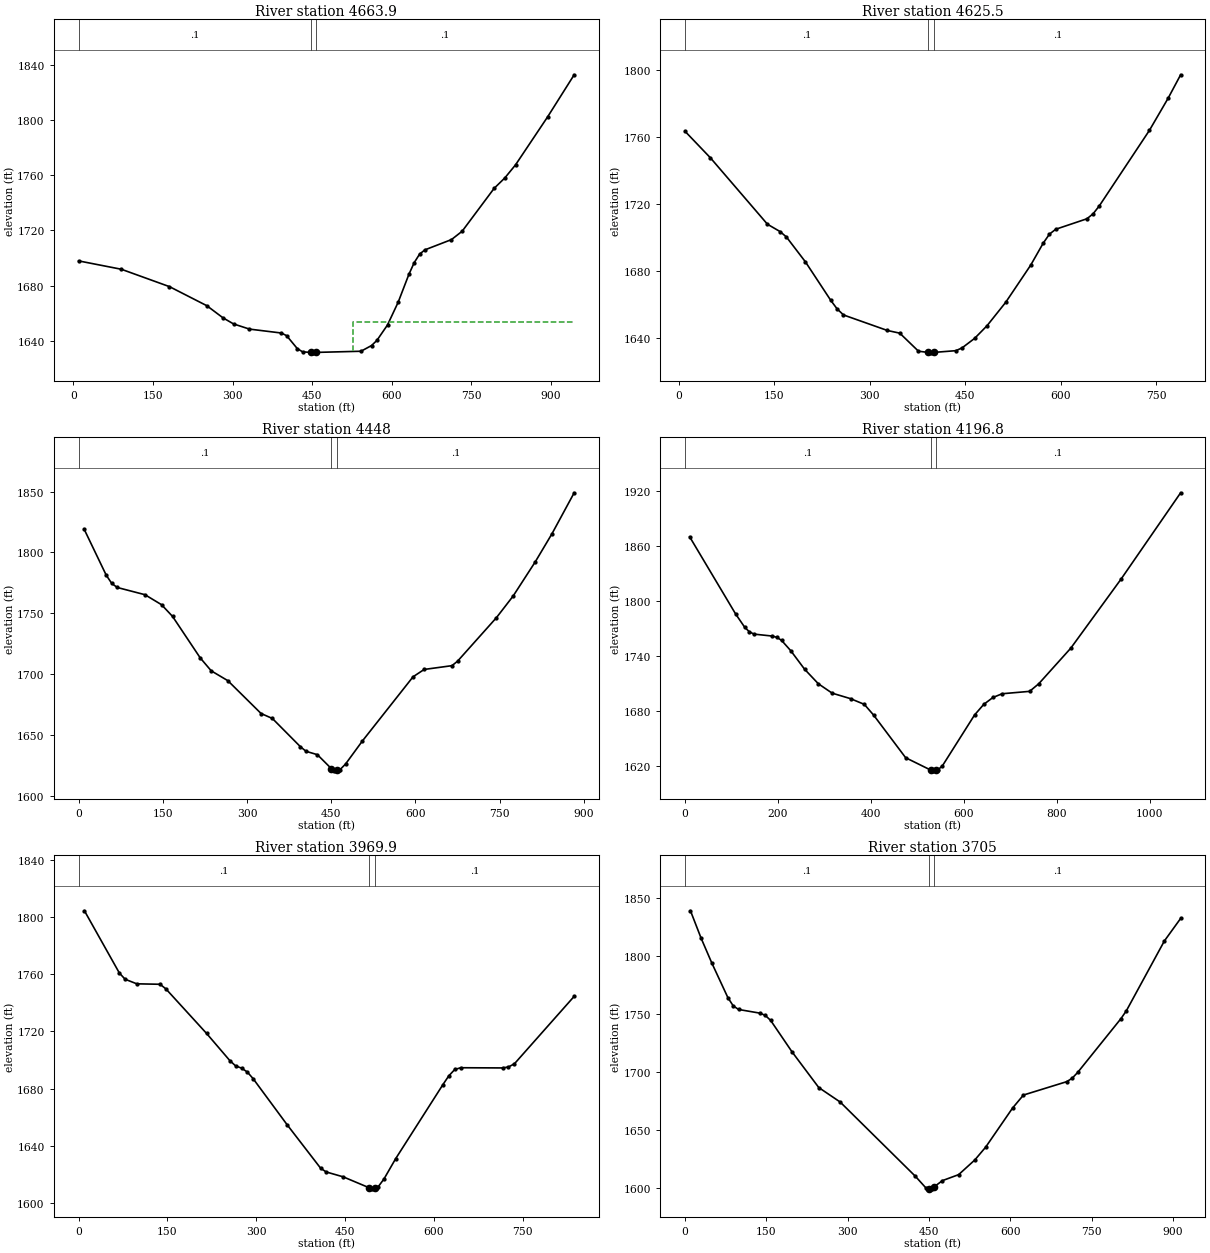
Type RM Length L Ch R = 1 ,4663.9  ,39.3,38.4,36.8
XS GIS Cut Line= 4
     1815928.499       121837.79     1815844.353      122117.276
     1815862.384      122426.813     1816024.666      122727.335
#Sta/Elev= 30
    10.1    1698    90.6 1691.95   181.2 1679.38   251.6 1665.58   281.8 1656.87
   301.9  1652.4   331.9 1648.66   391.9 1645.83   401.9  1643.9   421.9 1634.59
   431.9 1632.22   446.9 1631.81  452.02 1631.49   456.9  1631.8   541.9 1632.64
   561.9 1636.79   571.9 1640.48   591.9 1651.66     612 1668.12   632.1 1688.19
   642.1 1696.68   652.2 1702.82   662.2 1705.97   712.4 1713.42   732.5 1719.46
   792.8 1750.51   812.9 1758.02     833 1767.45   893.3 1802.08   943.5 1832.64
#Mann= 3 , 0 , 0
    10.1      .1       0   446.9    .045       0   456.9      .1       0
#XS Ineff= 2 , 0
                          526.67          1653.6
Permanent Ineff=
       F       F
Bank Sta=446.9,456.9
XS Rating Curve= 0 ,0
Exp/Cntr=0.3,0.1

Type RM Length L Ch R = 1 ,4625.5  ,184.1,177.5,171
XS GIS Cut Line= 4
     1815635.556      121962.479     1815810.361      122179.544
     1815833.412      122433.106     1815929.458      122669.381
#Sta/Elev= 30
      10 1763.22    49.8 1747.46   139.4 1707.95   159.3 1703.57   169.2 1700.36
   199.1 1685.52   238.9 1662.61   248.8 1657.58   258.8 1653.98   327.7 1644.74
   347.2 1643.14   376.6  1632.4   391.2 1631.71  396.25 1631.43   401.2  1631.7
   435.4 1632.72   445.2 1634.41   464.8 1640.04   484.3 1647.57   513.7 1661.54
   552.9 1683.63   572.5 1696.68   582.4  1702.1   592.2 1704.97   641.2 1711.21
     651 1714.21   660.8 1718.97   739.3 1763.79   768.7 1782.92   788.4  1796.9
#Mann= 3 , 0 , 0
      10      .1       0   391.2    .045       0   401.2      .1       0
Bank Sta=391.2,401.2
XS Rating Curve= 0 ,0
Exp/Cntr=0.3,0.1

Type RM Length L Ch R = 1 ,4448    ,255,251.1,247.3
XS GIS Cut Line= 4
     1815447.305      121991.293     1815614.426      122258.302
     1815721.998      122517.627      1815892.96      122748.139
#Sta/Elev= 30
     9.8 1819.14    49.2  1781.3    59.1 1774.51    68.9 1771.22   118.1 1765.31
   147.7 1757.08   167.3 1747.46   216.6 1713.37   236.2 1702.74   265.8 1694.65
     325 1667.67   345.1 1663.61   395.2 1640.32   405.2  1636.6   425.3 1633.85
   450.4 1622.29   455.4 1620.57   460.4 1621.02   465.4 1621.46   475.4 1626.13
   505.5 1645.13   595.7 1697.84   615.5 1703.88     665 1706.99   674.9 1710.63
   744.2 1746.42   773.9 1764.15   813.5 1792.38   843.2 1815.41   882.7 1849.05
#Mann= 3 , 0 , 0
       0      .1       0   450.4    .045       0   460.4      .1       0
Bank Sta=450.4,460.4
XS Rating Curve= 0 ,0
Exp/Cntr=0.3,0.1

Type RM Length L Ch R = 1 ,4196.8  ,225.7,227,228.3
XS GIS Cut Line= 4
     1815261.461      122010.976     1815381.829      122408.715
      1815529.55      122631.205     1815813.585      122890.188
#Sta/Elev= 30
     9.9 1870.38   108.8 1786.17   128.6 1771.47   138.5  1766.7   148.4 1764.18
     188 1762.03   197.9 1760.57   207.8  1757.3   227.6    1746   257.2 1725.89
   286.9 1709.95   316.6  1699.7   356.2 1693.68   385.9 1687.45   405.7 1675.87
   474.9 1629.17   529.2 1615.59   534.2 1614.84   539.2 1615.36   544.1 1615.86
     554 1620.28   623.3 1675.87   643.1 1687.46   662.8 1694.95   682.6 1699.04
   741.8 1701.66   761.5 1709.95   830.5 1748.86   938.9  1824.4    1067 1918.55
#Mann= 3 , 0 , 0
       0      .1       0   529.2    .045       0   539.2      .1       0
Bank Sta=529.2,539.2
XS Rating Curve= 0 ,0
Exp/Cntr=0.3,0.1

Type RM Length L Ch R = 1 ,3969.9  ,265.4,264.8,264.3
XS GIS Cut Line= 5
     1815057.357      122206.437     1815203.347      122484.971
     1815245.608      122600.227     1815314.761      122719.325
     1815493.407      122911.417
#Sta/Elev= 30
     9.8 1804.27    68.8 1760.82    78.6 1756.43    98.3 1753.26   137.6 1752.94
   147.4 1749.74   216.2  1718.6   255.5 1699.62   265.3 1695.92   275.2 1694.39
     285 1691.67   294.8 1687.04   352.2 1654.88   408.9 1624.47   418.3 1621.86
   447.1 1618.44   491.3 1610.76   496.3 1610.07   501.3  1610.8   506.1  1611.5
   515.9 1616.93   535.6 1631.09   615.3 1682.72   625.4 1688.95   635.5 1693.42
   645.6 1694.65   716.2 1694.51   726.3 1695.18   736.4 1697.44   837.3  1744.5
#Mann= 3 , 0 , 0
       0      .1       0   491.3    .045       0   501.3      .1       0
Bank Sta=491.3,501.3
XS Rating Curve= 0 ,0
Exp/Cntr=0.3,0.1

Type RM Length L Ch R = 1 ,3705    ,401.8,399.3,396.8
XS GIS Cut Line= 4
     1814795.853      122374.905     1814978.858      122667.768
     1815109.693      122879.721     1815243.803      123170.338
#Sta/Elev= 30
     9.9 1839.23    29.6 1815.55    49.3 1794.22    78.9 1764.44    88.8 1757.29
    98.7 1754.18   138.1 1751.02     148 1749.08   157.9 1744.75   197.3 1717.69
   246.7 1686.89   286.1 1674.46     425 1610.42     445  1600.1   449.9 1599.87
   454.9 1599.62   459.9 1601.46   474.9 1606.71   504.8 1611.85   534.6 1624.48
   554.6  1635.5   604.4 1669.28   624.4 1680.44   704.4 1691.99   714.4 1694.98
   724.4 1699.88   804.5 1746.38   814.5  1753.2   884.5 1813.23   914.5 1832.64
#Mann= 3 , 0 , 0
       0      .1       0   449.9    .045       0   459.9      .1       0
Bank Sta=449.9,459.9
XS Rating Curve= 0 ,0
Exp/Cntr=0.3,0.1

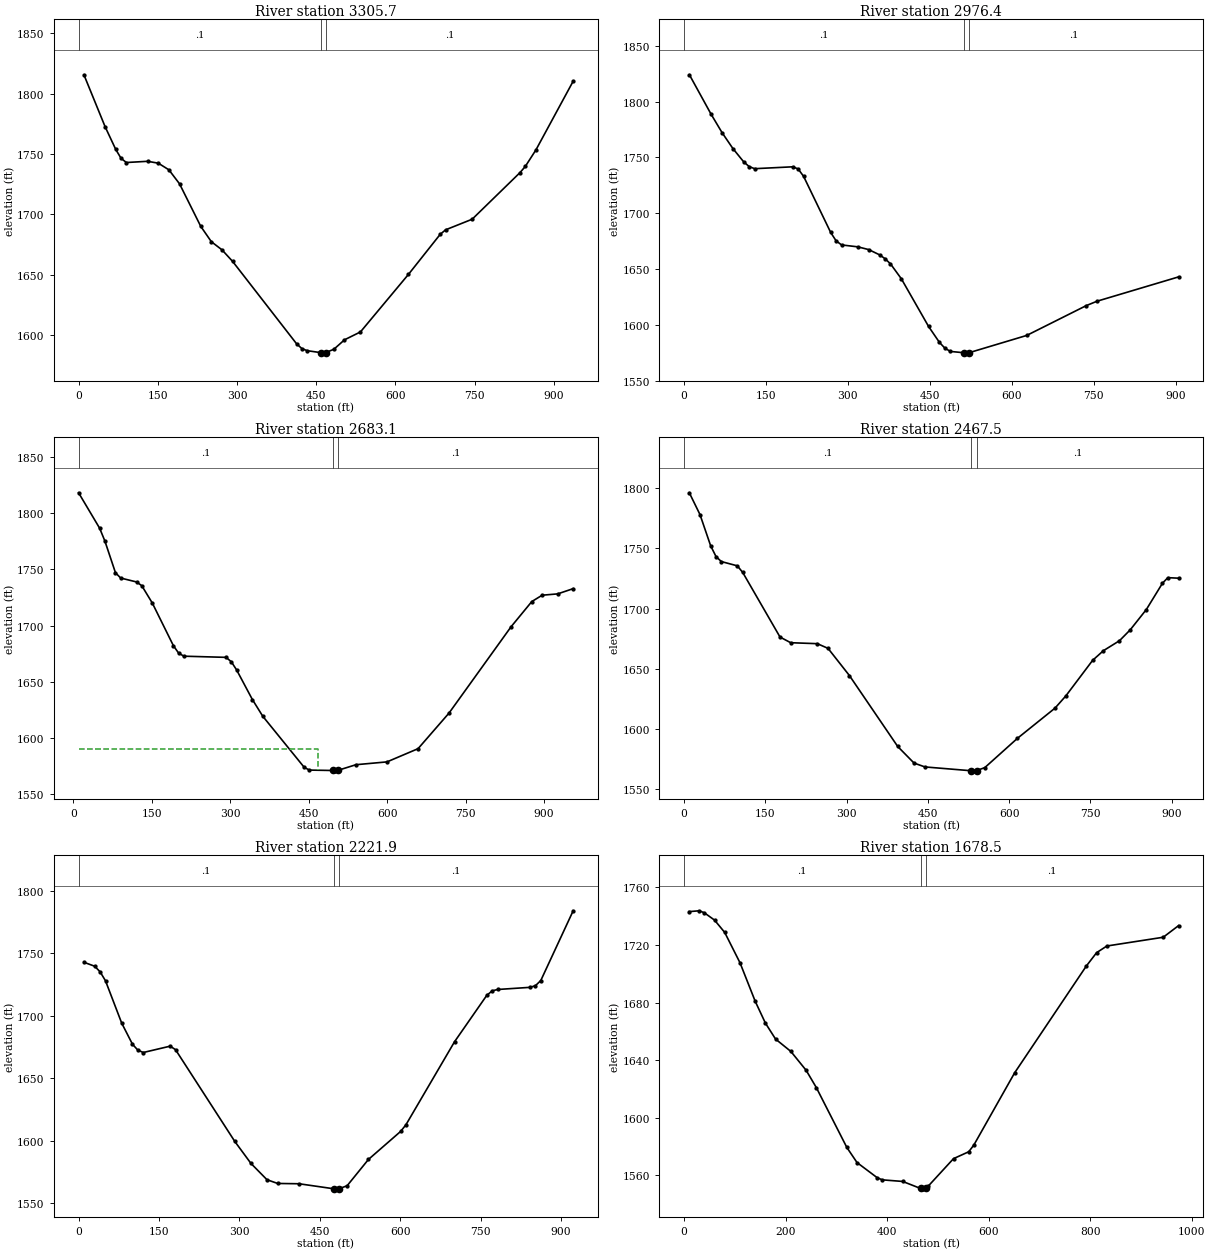
Type RM Length L Ch R = 1 ,3305.7  ,317.2,329.3,341.4
XS GIS Cut Line= 4
     1814457.273      122626.095     1814633.453      122895.421
     1814798.305      123099.524     1815114.926      123253.909
#Sta/Elev= 30
    10.1 1815.53    50.3 1772.47    70.4 1753.72    80.5 1746.34    90.5 1742.92
   130.7 1743.92   150.9 1742.37     171 1736.87   191.1 1725.31   231.3  1690.1
   251.4 1677.37   271.5 1670.66   291.7 1661.05   412.7 1592.93   422.7 1588.96
   432.8 1587.19   458.1  1585.6   463.1  1585.4   468.1 1585.67   483.3 1588.33
   503.5 1596.18   533.7  1602.7   624.5 1650.28   684.8 1683.52   694.9  1687.2
   745.2 1695.98   835.8 1734.55   845.9  1739.7     866 1753.36   936.5 1810.23
#Mann= 3 , 0 , 0
       0      .1       0   458.1    .045       0   468.1      .1       0
Bank Sta=458.1,468.1
XS Rating Curve= 0 ,0
Exp/Cntr=0.3,0.1

Type RM Length L Ch R = 1 ,2976.4  ,285.2,293.3,300.9
XS GIS Cut Line= 4
     1814416.267      122623.284       1814421.5      123021.023
     1814442.434      123269.609     1814541.869      123507.729
#Sta/Elev= 30
     9.9 1824.05    49.7 1788.61    69.6 1772.24    89.5 1757.95   109.4 1745.95
   119.3 1741.78   129.3  1739.9   198.9 1741.58   208.8 1739.73   218.8 1733.14
   268.5 1682.75   278.4 1675.24   288.4 1671.58   318.2 1669.86   338.1  1667.4
     358  1662.7   367.9 1659.26   377.9 1654.65   397.8 1641.27   447.7 1598.49
   467.6 1584.21   477.6 1579.03   487.6 1576.15   512.5 1574.95   517.5 1574.88
   522.5 1575.11   627.3 1590.48   736.6 1617.27   756.4  1621.2   905.3 1642.94
#Mann= 3 , 0 , 0
       0      .1       0   512.5    .045       0   522.5      .1       0
Bank Sta=512.5,522.5
XS Rating Curve= 0 ,0
Exp/Cntr=0.3,0.1

Type RM Length L Ch R = 1 ,2683.1  ,204.9,215.7,226.8
XS GIS Cut Line= 4
       1814374.4      122623.284     1814200.908       122930.14
     1814123.197      123164.941     1814047.112      123512.703
#Sta/Elev= 30
    10.1 1818.19    50.4  1786.6    60.4 1775.22    80.6 1747.03    90.6 1742.28
   120.9  1738.8   130.9 1735.49   151.1    1720   191.4 1682.07   201.4 1675.44
   211.5 1672.71   292.1 1671.67   302.1 1667.76   312.2 1660.54   342.4 1634.13
   362.4 1619.16   441.5 1573.77   451.4 1571.31   495.9 1570.95   500.9 1570.64
   505.9 1571.07   540.5  1576.1   599.8 1578.61   659.2 1590.37   718.5 1622.12
   837.2    1699   876.7 1721.35   896.5    1727   926.2 1728.18   955.8 1732.84
#Mann= 3 , 0 , 0
    10.1      .1       0   495.9    .045       0   505.9      .1       0
#XS Ineff= 2 , 0
           467.6 1590.04
Permanent Ineff=
       F       F
Bank Sta=495.9,505.9
XS Rating Curve= 0 ,0
Exp/Cntr=0.3,0.1

Type RM Length L Ch R = 1 ,2467.5  ,244.2,245.6,247
XS GIS Cut Line= 4
     1814321.641      122579.097     1814098.814      122867.236
     1813916.326      123024.752     1813745.363      123280.236
#Sta/Elev= 30
     9.8  1796.1    29.5 1778.01    49.2 1752.11    59.1 1743.17    68.9 1739.04
    98.4  1735.5   108.3 1730.07   177.2 1676.42   196.9 1671.73   246.1 1670.93
   265.8 1667.04   305.2 1644.52   394.4 1585.64   424.5 1571.89   444.6 1568.69
     530 1565.52     535 1565.45     540 1565.67   555.1 1568.13   615.2 1592.38
   684.6 1617.45   704.5 1627.53   754.1 1657.12   773.9  1665.1   803.6 1673.38
   823.5 1682.44   853.2 1699.27     883 1721.11   892.9  1725.7   912.7 1725.25
#Mann= 3 , 0 , 0
       0      .1       0     530    .045       0     540      .1       0
Bank Sta=530,540
XS Rating Curve= 0 ,0
Exp/Cntr=0.3,0.1

Type RM Length L Ch R = 1 ,2221.9  ,556.5,543.4,527.5
XS GIS Cut Line= 4
     1814233.098      122505.533     1813962.428      122678.985
     1813747.284      122840.343     1813499.484       123061.25
#Sta/Elev= 30
      10 1742.73    30.1 1739.55    40.2 1735.04    50.2 1727.89    80.4 1694.02
   100.5 1677.12   110.5 1672.41   120.6 1670.48   170.8 1675.57   180.8 1672.75
   291.3  1599.3   321.5 1581.66   351.4 1568.62   371.3 1565.64   411.1  1565.4
   475.8 1561.39   480.8 1561.33   485.8 1561.42   500.8  1563.8   540.6 1584.88
   600.5 1607.26   610.5 1612.61   701.1 1679.08   761.4 1716.32   771.5 1719.87
   781.5 1720.94   841.9 1722.66     852 1723.97     862 1728.12   922.4 1783.96
#Mann= 3 , 0 , 0
       0      .1       0   475.8    .045       0   485.8      .1       0
Bank Sta=475.8,485.8
XS Rating Curve= 0 ,0
Exp/Cntr=0.3,0.1

Type RM Length L Ch R = 1 ,1678.5  ,198.7,194.9,191.2
XS GIS Cut Line= 4
      1813636.49      121953.409     1813511.698      122248.896
     1813479.488        122547.4     1813482.105      122900.654
#Sta/Elev= 30
      10 1743.17    30.1 1743.76    40.1 1742.35    60.1  1737.3    80.2 1728.72
   110.3 1707.65   140.3 1680.86   160.4  1665.7   180.4 1654.63   210.5 1646.05
   240.6 1632.94   260.6 1620.99   320.8 1579.34   340.8 1568.87   380.8 1558.28
   390.8 1556.84   430.8 1555.74   465.9 1550.88   470.9  1550.6   475.9  1551.5
   480.9  1552.4   530.9 1571.57   560.9 1576.36     571 1581.04   651.3 1631.18
   792.6 1705.41   812.8 1714.66     833 1719.29     944 1725.37   974.3 1733.46
#Mann= 3 , 0 , 0
       0      .1       0   465.9    .045       0   475.9      .1       0
Bank Sta=465.9,475.9
XS Rating Curve= 0 ,0
Exp/Cntr=0.3,0.1

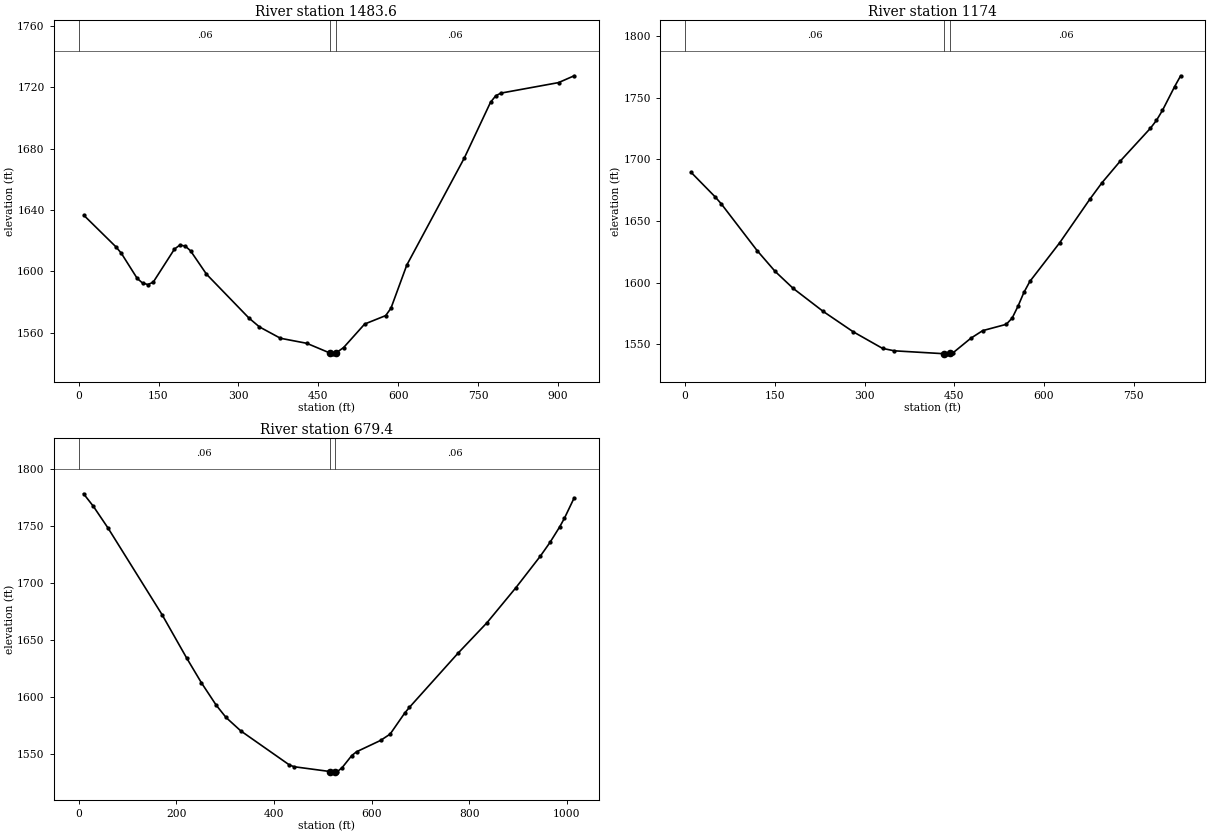
Type RM Length L Ch R = 1 ,1483.6  ,320.2,309.6,299.1
XS GIS Cut Line= 4
     1813353.887      121911.542     1813288.469      122194.145
     1813314.636      122529.083     1813440.238      122806.453
#Sta/Elev= 30
      10 1636.48      70 1616.02      80 1611.91     110 1595.43     120 1592.44
     130 1591.45     140 1592.95     180 1614.57     190 1617.14   200.1 1616.53
   210.1 1613.43   240.1 1598.18   319.7 1569.66   339.5 1563.85     379 1556.45
   428.4 1553.17   472.8  1546.7   477.8 1546.31   482.8 1546.77   497.6 1550.42
   537.1 1565.72   576.6 1571.22   586.5 1576.05   616.2 1604.13   724.3 1673.92
   773.4 1710.14   783.2 1714.39     793 1716.13   901.1 1722.97   930.5 1727.42
#Mann= 3 , 0 , 0
       0     .06       0   472.8    .045       0   482.8     .06       0
Bank Sta=472.8,482.8
XS Rating Curve= 0 ,0
Exp/Cntr=0.3,0.1

Type RM Length L Ch R = 1 ,1174    ,494.9,494.5,494.1
XS GIS Cut Line= 4
     1812790.593       122177.97     1812958.765      122390.398
     1813134.084      122675.618     1813301.553      122822.153
#Sta/Elev= 30
      10 1689.45    50.2 1669.57    60.2 1664.07   120.4 1626.02   150.5 1609.16
   180.6 1595.42   230.8 1576.75   280.8 1560.29     330 1546.78   349.7 1544.81
   433.3 1542.44   438.3 1542.36   443.3 1542.85   448.2 1543.34   477.7 1555.03
   497.4 1561.16   536.8 1566.27   546.7 1571.35   556.5    1581   566.3  1592.1
   576.2 1600.99     626 1632.29   676.5 1667.65   696.8    1681   727.1  1698.4
   777.7 1725.12   787.8 1731.49   797.9 1739.62   818.1 1758.77   828.3 1767.68
#Mann= 3 , 0 , 0
       0     .06       0   433.3    .045       0   443.3     .06       0
Bank Sta=433.3,443.3
XS Rating Curve= 0 ,0
Exp/Cntr=0.3,0.1

Type RM Length L Ch R = 1 ,679.4   ,678.2,679.4,680.7
XS GIS Cut Line= 4
     1812464.209      122343.297      1812574.11      122709.635
     1812722.584      122941.294     1812990.166      123178.025
#Sta/Elev= 30
    10.1 1778.13    30.2 1767.14    60.4 1747.99   171.1 1672.07   221.4 1634.15
   251.6 1612.48   281.8 1592.94   301.9 1582.18   332.1 1570.42   431.6 1540.61
   441.4 1539.03     515 1534.82     520 1534.56     525 1534.66   529.9 1534.76
   539.7 1538.26   559.4 1548.84   569.2 1552.15   618.3 1562.06     638 1567.63
   667.5 1585.84   677.5 1591.06   776.7 1638.34   836.3 1665.18   895.8 1696.01
   945.4 1723.38   965.3 1735.48   985.1 1749.05     995 1756.75  1014.9 1774.55
#Mann= 3 , 0 , 0
       0     .06       0     515    .045       0     525     .06       0
Bank Sta=515,525
XS Rating Curve= 0 ,0
Exp/Cntr=0.3,0.1

Chan Stop Cuts=-1
Use User Specified Reach Order=0